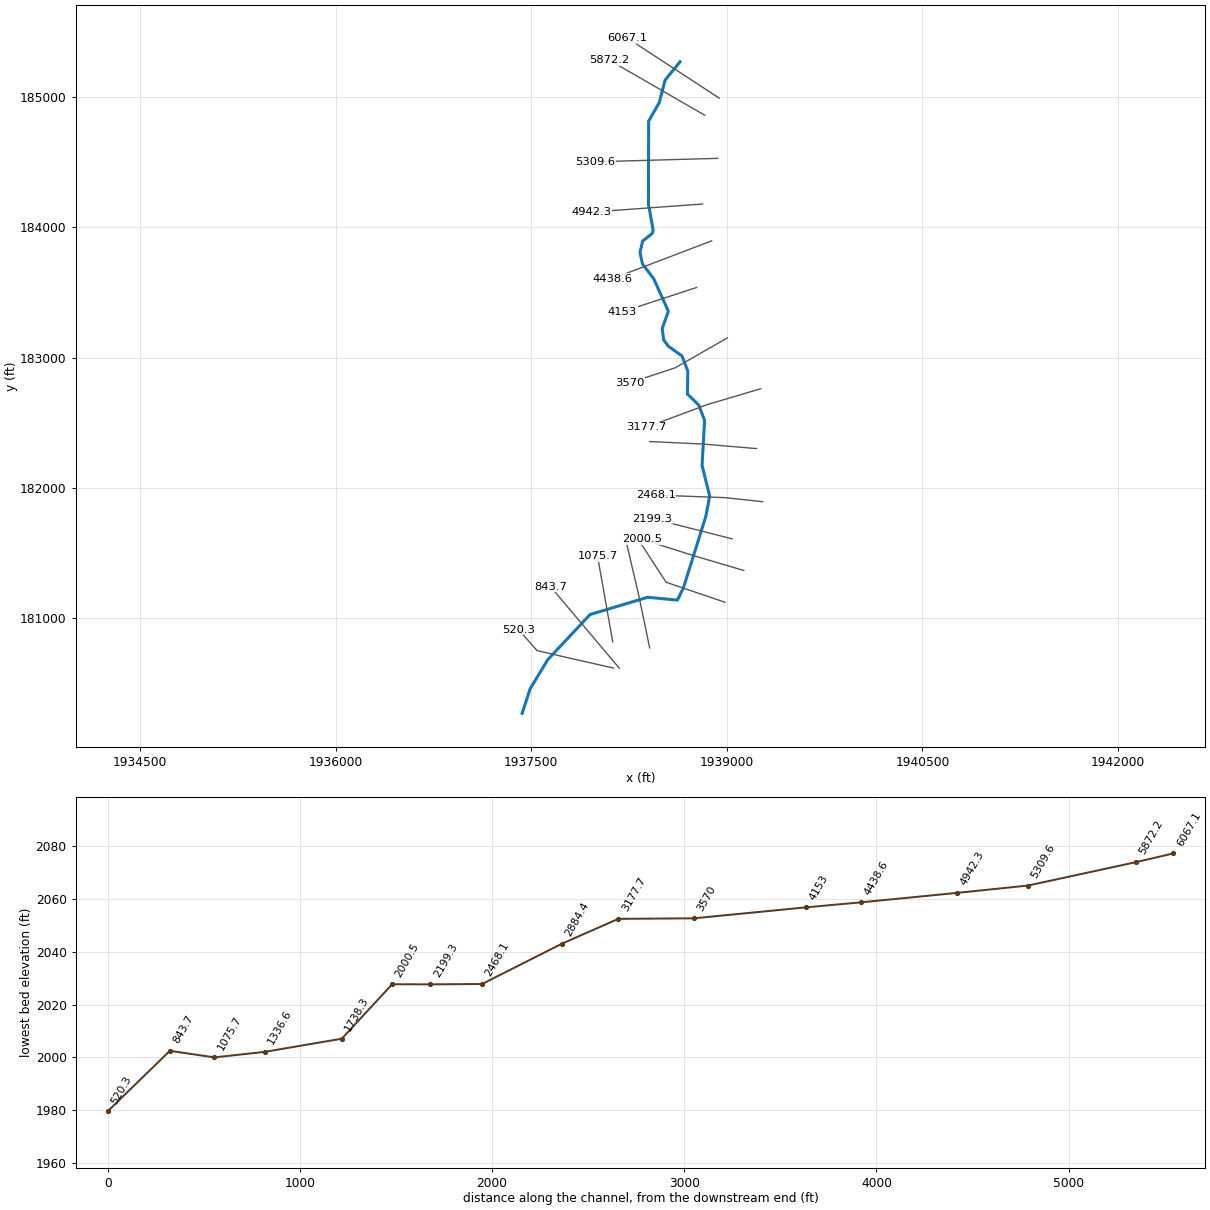
--- TrcCrk.prj (project) ---

Proj Title=TrcCrk
Current Plan=p01
Default Exp/Contr=0,0
English Units
Geom File=g01
Flow File=f01
Plan File=p01
BEGIN DESCRIPTION:
END DESCRIPTION:
DSS Export Rating Curves= 0
DSS Export Rating Curve Sorted= 0
DSS Export Volume Flow Curves= 0
DXF OffsetX= 0
DXF OffsetY= 0
DXF ScaleX= 0
DXF ScaleY= 0

--- TrcCrk.p01 (plan) ---

Plan Title=Floodplain
Program Version=4.00
Geom File=g01
Flow File=f01
K Sum by GR=0
Std Step Tol=0.01
Critical Tol=0.01
Num of Std Step Trials=20
Max Error Tol=0.3
Flow Tol Ratio=0.001
Split Flow NTrial=30
Split Flow Tol=0.02
Split Flow Ratio=0.02
Log Output Level=0
Friction Slope Method=1
Unsteady Friction Slope Method=2
Unsteady Bridges Friction Slope Method=1
Global Log Level=0
CheckData=False
Run HTab=0
Run UNet=0
Run PostProcess=0
UNET Theta=0
UNET Theta Warmup=0
UNET ZTol=0
UNET ZSATol=0
UNET MxIter=0
UNET MaxInSteps=0
UNET DtIC=0
UNET DtMin=0
UNET MaxCRTS=0
UNET WFStab=0
UNET SFStab=0
UNET WFX=0
UNET SFX=0
UNET DSS MLevel=0
UNET DZMax Abort=0
UNET Convert EG Bridges=0
UNET Use Existing IB Tables=0
UNET Froude Limit=0
UNET Froude Power=0
Write IC File=0
Echo Input=False
Echo Output=False
Write Detailed=0

--- TrcCrk.f01 (steady flow) ---

Flow Title=NFF Regression Equation
Program Version=4.00
Number of Profiles=1
Profile Names=P100yr
River Rch & RM=TrcCrk,Main      ,6067.1
471.0776
River Rch & RM=TrcCrk,Main      ,5309.6
498.4059
River Rch & RM=TrcCrk,Main      ,3177.7
537.6899
River Rch & RM=TrcCrk,Main      ,2884.4
596.3137
Boundary for River Rch & Prof#=TrcCrk,Main      ,1
Up Type=0
Dn Type=3
Dn Slope=0.022713

--- TrcCrk.g01 (geometry) ---

Geom Title=USGS 3m DEM
Program Version=4.10

River Reach=TrcCrk          ,Main
Reach XY= 30
      1938641.03      185273.911     1938526.571      185133.358
     1938481.223      184959.133      1938400.32      184817.841
     1938398.663      184178.873     1938434.586       183980.85
     1938429.376      183955.842     1938354.294      183895.927
     1938333.917      183808.862     1938352.442      183719.945
     1938439.506      183605.093      1938551.31      183355.878
     1938504.342      183222.795     1938515.456       183135.73
     1938551.782      183086.701     1938656.242      183012.311
     1938700.701      182895.608     1938697.654      182719.265
     1938783.979      182635.855     1938829.266      182517.819
     1938809.995      182171.302     1938868.453      181934.811
     1938839.122      181780.081     1938667.007       181229.93
     1938620.372       181135.55      1938392.87      181157.458
     1937950.461       181024.64     1937626.882      180678.518
     1937491.466       180454.56     1937429.606      180264.862

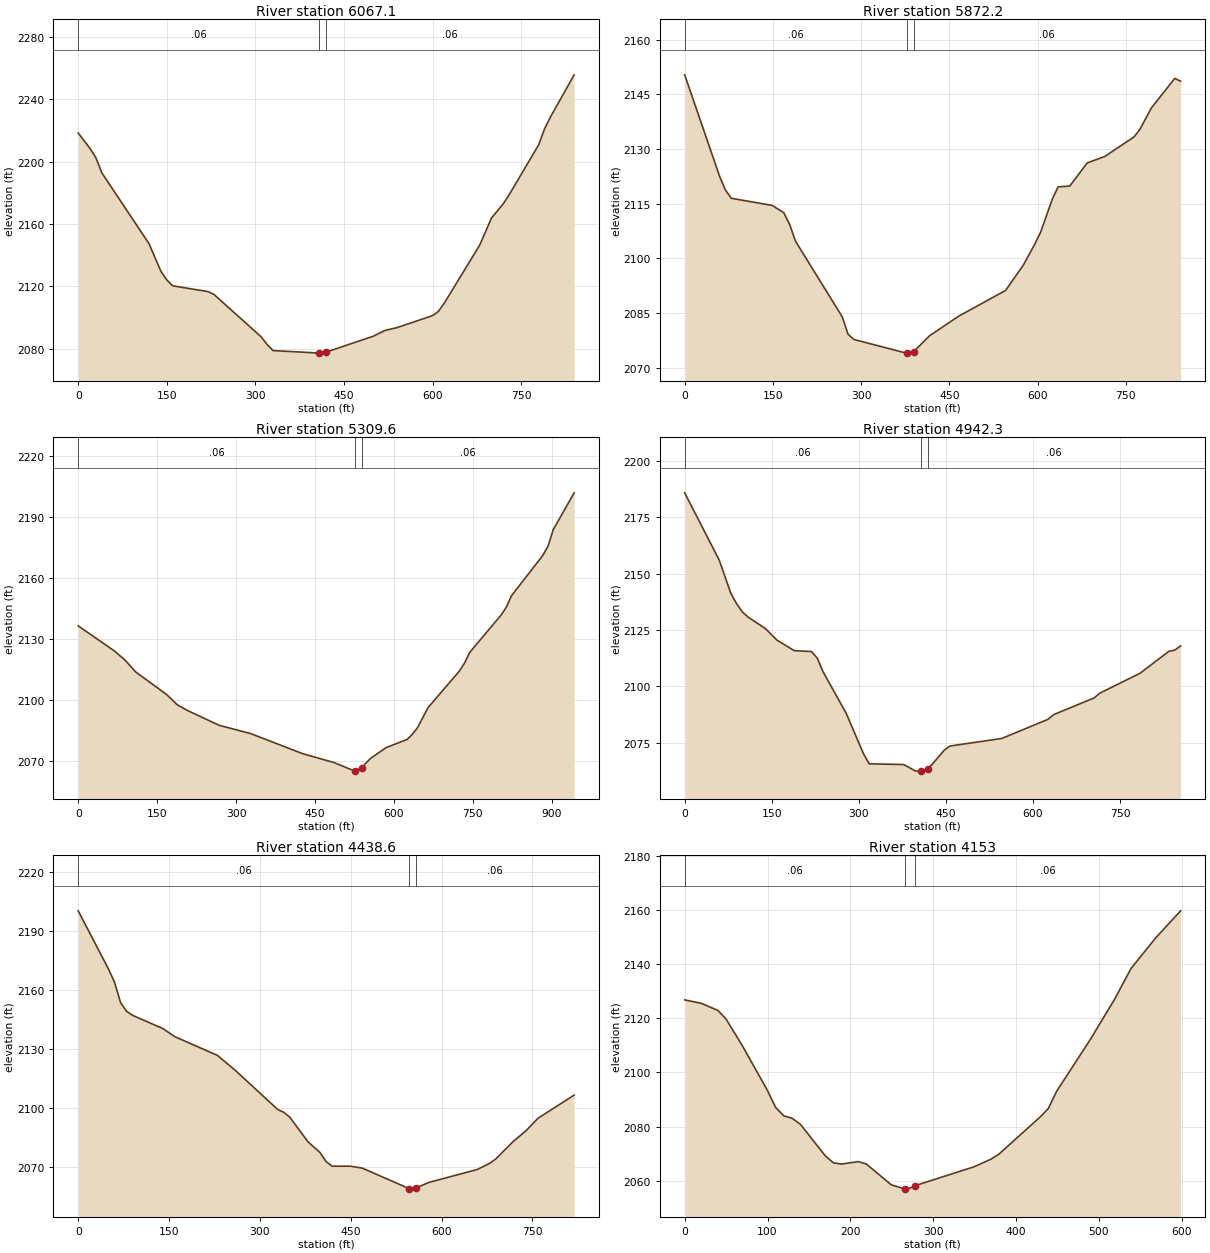
Type RM Length L Ch R = 1 ,6067.1  ,194,194.9,195.9
XS GIS Cut Line= 2
      1938941.89      184994.077     1938239.443      185453.831
#Sta/Elev= 30
       0  2218.3      20 2208.44      30 2202.43      40 2192.78   119.9 2147.39
   139.9 2129.81   149.9 2124.19   159.9 2120.44   219.9  2116.7   229.9 2114.88
   309.8 2087.72   319.8 2082.78   329.8 2078.96   407.9 2077.36   409.8 2077.32
   419.9    2078   499.7 2088.18   519.7  2091.9   539.7 2093.66   599.7 2101.34
   609.7 2104.02   619.6  2109.3   679.6 2146.48   699.6 2163.85   719.6 2173.04
   729.6 2178.81   779.6 2210.82   789.6 2221.16   799.6 2228.66   839.5 2255.56
#Mann= 3 , 0 , 0
       0     .06       0   407.9    .045       0   419.9     .06       0
Bank Sta=407.9,419.9
XS Rating Curve= 0 ,0
Exp/Cntr=0.3,0.1

Type RM Length L Ch R = 1 ,5872.2  ,550.4,562.4,574.5
XS GIS Cut Line= 2
     1938830.372      184862.902     1938100.509      185285.259
#Sta/Elev= 30
       0 2150.39    59.5 2122.48    69.4 2118.74    79.4  2116.5   148.8 2114.55
   168.6 2112.54   178.6 2109.29   188.5 2104.72   267.9 2083.98   277.8  2079.2
   287.7 2077.76     377 2074.01   377.2 2074.01   389.2 2074.41   416.7 2078.81
   466.3 2084.19   545.6  2091.2   575.4 2098.06   595.2 2103.87   605.2 2107.18
     625 2116.23   634.9 2119.64   654.8 2119.86   684.5 2126.22   714.3 2127.98
   763.9 2133.33   773.8 2135.34   793.6  2141.3   833.3 2149.41   843.3 2148.64
#Mann= 3 , 0 , 0
       0     .06       0   377.2    .045       0   389.2     .06       0
Bank Sta=377.2,389.2
XS Rating Curve= 0 ,0
Exp/Cntr=0.3,0.1

Type RM Length L Ch R = 1 ,5309.6  ,366.4,367.3,368.2
XS GIS Cut Line= 2
     1938930.404      184531.314     1937988.079      184504.727
#Sta/Elev= 30
       0 2136.46    69.5    2124    89.3 2119.57   109.2 2113.84   168.7 2102.62
   188.5 2097.66   208.4 2094.82   267.9 2087.62   327.5 2083.59   426.7 2073.69
   486.2 2069.33   525.9 2065.12   526.6 2065.19   538.6 2066.82   555.7 2071.38
   585.5 2076.68   625.2 2080.69   635.1 2083.15     645 2086.48   664.8 2096.22
   724.4 2114.23   734.3 2118.16   744.2 2123.42   803.8 2141.76   813.7 2145.57
   823.6 2151.25   883.2 2171.09   893.1 2175.62     903 2183.74   942.7 2201.79
#Mann= 3 , 0 , 0
       0     .06       0   526.6    .045       0   538.6     .06       0
Bank Sta=526.6,538.6
XS Rating Curve= 0 ,0
Exp/Cntr=0.3,0.1

Type RM Length L Ch R = 1 ,4942.3  ,498.6,503.7,508.5
XS GIS Cut Line= 2
     1938813.592      184180.273     1937961.576       184118.22
#Sta/Elev= 30
       0 2185.81    59.6 2155.91    79.5 2141.22    89.4 2136.63    99.3 2133.01
   109.3 2130.68   139.1 2125.59   158.9 2120.48   188.7 2115.81   218.5  2115.4
   228.5 2112.46   238.4 2106.42   278.1 2088.09   307.9 2070.14   317.9  2065.6
   377.5 2065.29   397.3 2062.42     407 2062.36     419 2063.22     447 2071.62
   456.9 2073.48   546.3 2076.86   625.8 2085.33   635.7 2087.43   705.3 2094.83
   715.2 2096.96   784.7 2105.82   834.4 2115.56   844.3 2116.04   854.3 2117.94
#Mann= 3 , 0 , 0
       0     .06       0     407    .045       0     419     .06       0
Bank Sta=407,419
XS Rating Curve= 0 ,0
Exp/Cntr=0.3,0.1

Type RM Length L Ch R = 1 ,4438.6  ,286.5,285.7,284.8
XS GIS Cut Line= 3
     1938883.782      183897.129     1938501.253      183750.974
     1938118.723      183604.818
#Sta/Elev= 30
       0 2200.43    49.9 2170.85    59.9 2164.18    69.9 2153.76    79.9 2149.28
    89.9  2147.2   139.8 2140.47   159.8 2136.32   229.7 2126.86   259.7 2119.12
   329.6 2099.26   339.6 2097.84   349.6 2095.28   379.5 2082.82   399.5 2077.32
   409.5 2072.71   419.5  2070.4   449.4 2070.42   469.4 2069.41   546.6    2059
   549.3 2058.74   558.6 2059.45   579.3 2062.18   659.2 2068.76   679.2 2071.81
   689.2 2073.98   719.1 2083.24   739.1 2088.32   759.1 2094.78     819 2106.61
#Mann= 3 , 0 , 0
       0     .06       0   546.6    .045       0   558.6     .06       0
Bank Sta=546.6,558.6
XS Rating Curve= 0 ,0
Exp/Cntr=0.3,0.1

Type RM Length L Ch R = 1 ,4153    ,579,582.8,586.6
XS GIS Cut Line= 2
     1938767.389      183538.405     1938198.395       183351.81
#Sta/Elev= 30
       0 2126.83      20 2125.57    39.9 2122.97    49.9 2119.79    69.9 2109.74
    99.8 2093.41   109.8 2087.08   119.8 2083.93   129.7 2083.08   139.7 2080.83
   169.7  2069.2   179.6 2066.57   189.6 2066.12   209.6 2067.03   219.6 2066.09
   249.5 2058.43   266.3 2056.87   269.5 2056.85   278.3 2058.14   349.3  2065.1
   369.3 2067.85   379.2 2069.74   429.2 2083.53   439.1 2086.68   449.1 2093.04
     489 2111.81     519 2127.01   538.9 2138.44   568.9 2149.83   598.8 2159.77
#Mann= 3 , 0 , 0
       0     .06       0   266.3    .045       0   278.3     .06       0
Bank Sta=266.3,278.3
XS Rating Curve= 0 ,0
Exp/Cntr=0.3,0.1

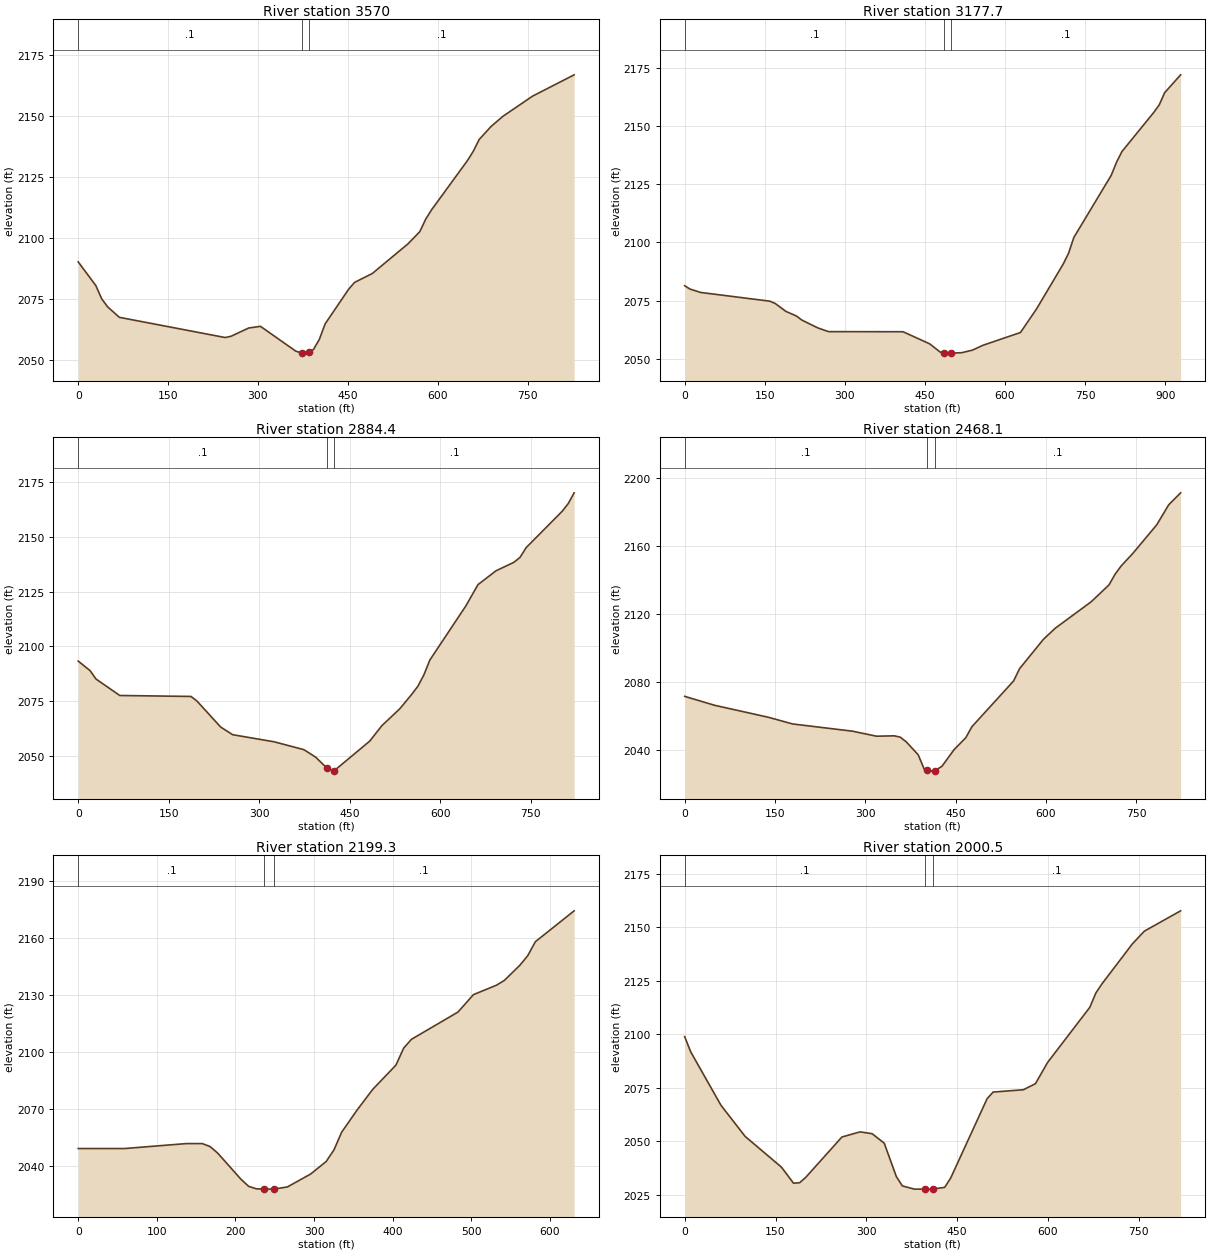
Type RM Length L Ch R = 1 ,3570    ,394.2,392,389.4
XS GIS Cut Line= 3
       1939004.2      183151.334     1938604.374      182921.542
     1938256.464      182806.185
#Sta/Elev= 30
       0 2090.15    29.4 2080.44    39.2 2074.99    49.1  2071.7    68.7 2067.39
   245.3  2059.1   255.1 2059.62   284.5 2063.01   304.2 2063.69     363 2053.54
   372.8  2052.7   373.4  2052.7   385.4 2053.15   392.5 2054.15   402.3 2058.26
   412.1 2064.71   451.3 2078.92   461.2 2081.72   490.9  2085.4   550.3 2097.53
   570.1 2102.57     580  2107.7   589.9 2111.58   649.4 2131.66   659.3 2135.51
   669.2 2140.39     689 2145.72   708.8  2149.9   758.4  2158.2   827.7 2166.93
#Mann= 3 , 0 , 0
       0      .1       0   373.4    .045       0   385.4      .1       0
Bank Sta=373.4,385.4
XS Rating Curve= 0 ,0
Exp/Cntr=0.3,0.1

Type RM Length L Ch R = 1 ,3177.7  ,302.4,293.2,284.6
XS GIS Cut Line= 3
     1939260.138      182760.379     1938848.896      182638.118
     1938380.528      182463.116
#Sta/Elev= 30
       0 2081.42      10    2080    29.9 2078.55   159.6  2074.8   169.6 2073.81
   189.6 2070.42   209.5 2068.42   219.5 2066.69   249.4 2063.33   269.4 2061.73
   409.1 2061.68     459 2056.48     479 2052.89   486.3 2052.61   498.3  2052.5
     519 2052.68     539 2053.78     559 2055.89     629 2061.35     659 2071.43
     709 2090.71     719 2095.32     729 2102.16     799 2128.83     809 2134.48
     819 2139.01     879 2155.92     889 2159.11     899 2164.28     929 2171.98
#Mann= 3 , 0 , 0
       0      .1       0   486.3    .045       0   498.3      .1       0
Bank Sta=486.3,498.3
XS Rating Curve= 0 ,0
Exp/Cntr=0.3,0.1

Type RM Length L Ch R = 1 ,2884.4  ,415.4,416.2,416.5
XS GIS Cut Line= 3
     1939227.192      182300.271     1938815.125      182335.353
     1938406.785      182354.427
#Sta/Elev= 30
       0 2093.33    19.7 2088.96    29.5 2085.14    68.9 2077.62   187.1 2077.18
   196.9 2075.08   236.3 2063.19     256 2059.73   324.9 2056.48   374.2 2052.89
   393.9 2049.43   412.7 2044.39   423.5 2043.09   424.7 2043.33   483.4  2056.8
   503.3 2063.79   533.2 2071.55   553.1 2078.18   563.1 2081.79   573.1 2086.99
     583 2093.79   642.9 2118.58   662.8 2128.22   692.7 2134.54   722.6 2138.45
   732.6 2140.68   742.6 2145.08   802.4  2161.7   812.4 2165.19   822.3 2170.14
#Mann= 3 , 0 , 0
       0      .1       0   412.7    .045       0   424.7      .1       0
Bank Sta=412.7,424.7
XS Rating Curve= 0 ,0
Exp/Cntr=0.3,0.1

Type RM Length L Ch R = 1 ,2468.1  ,273.3,268.9,264.4
XS GIS Cut Line= 3
     1939274.811      181892.065     1938987.829      181923.075
     1938453.338      181942.891
#Sta/Elev= 30
       0 2071.76    49.8  2066.5   139.4 2059.42   179.2 2055.53   278.7 2051.27
   318.4 2048.33   348.1 2048.54     358 2047.75   367.9 2045.02   387.7 2037.42
   397.6 2029.09   403.1 2028.36   407.5 2027.78   415.1 2027.96   427.3 2030.66
   447.1 2040.32   466.9 2047.49   476.8 2053.85   546.2 2080.83   556.1 2088.05
   595.7 2105.32   615.5 2111.88   674.9 2127.36   704.6 2137.32   714.6 2143.54
   724.5 2148.34   744.3  2155.9   783.9 2172.67   803.7 2184.42   823.5 2191.47
#Mann= 3 , 0 , 0
       0      .1       0   403.1    .045       0   415.1      .1       0
Bank Sta=403.1,415.1
XS Rating Curve= 0 ,0
Exp/Cntr=0.3,0.1

Type RM Length L Ch R = 1 ,2199.3  ,199.6,198.8,197.7
XS GIS Cut Line= 2
      1939041.55      181606.307     1938430.244      181761.913
#Sta/Elev= 30
       0 2049.05    59.1 2049.04     138 2051.66   157.7 2051.66   167.6 2050.11
   177.4 2046.65     207 2032.87   216.8 2029.12   226.7 2027.82   236.9 2027.69
   246.4 2027.66   248.9 2027.69   266.1 2028.82   295.7 2035.63   315.4 2042.22
   325.3 2048.33   335.1 2057.66   354.8 2069.35   374.5 2080.14   404.1 2092.96
     414 2101.94   423.8 2106.54     483  2120.9   502.7 2130.08   532.2 2135.09
   542.1  2137.6   561.8 2145.58   571.7 2150.56   581.5 2157.97   630.8 2174.22
#Mann= 3 , 0 , 0
       0      .1       0   236.9    .045       0   248.9      .1       0
Bank Sta=236.9,248.9
XS Rating Curve= 0 ,0
Exp/Cntr=0.3,0.1

Type RM Length L Ch R = 1 ,2000.5  ,262.8,262.1,261.7
XS GIS Cut Line= 3
     1939130.098      181363.379     1938737.449      181479.571
     1938347.237      181604.138
#Sta/Elev= 30
       0 2098.92      10  2091.8    59.9 2066.87    99.9  2052.3   159.8 2037.96
   179.8 2030.46   189.8 2030.68   199.8 2033.14   259.7 2052.03   289.6 2054.43
   309.6 2053.59   329.6 2049.14   349.6 2033.55   359.5  2029.2   379.5 2027.69
   397.4  2027.7   409.4  2027.7   429.5 2028.53   439.4  2032.9   499.4 2069.87
   509.4 2073.03   559.3  2074.1   579.3 2076.94   599.3 2086.82   669.2 2112.64
   679.2 2119.36   689.2 2123.57   739.2 2142.16   759.2 2148.19   819.1 2157.68
#Mann= 3 , 0 , 0
       0      .1       0   397.4    .045       0   409.4      .1       0
Bank Sta=397.4,409.4
XS Rating Curve= 0 ,0
Exp/Cntr=0.3,0.1

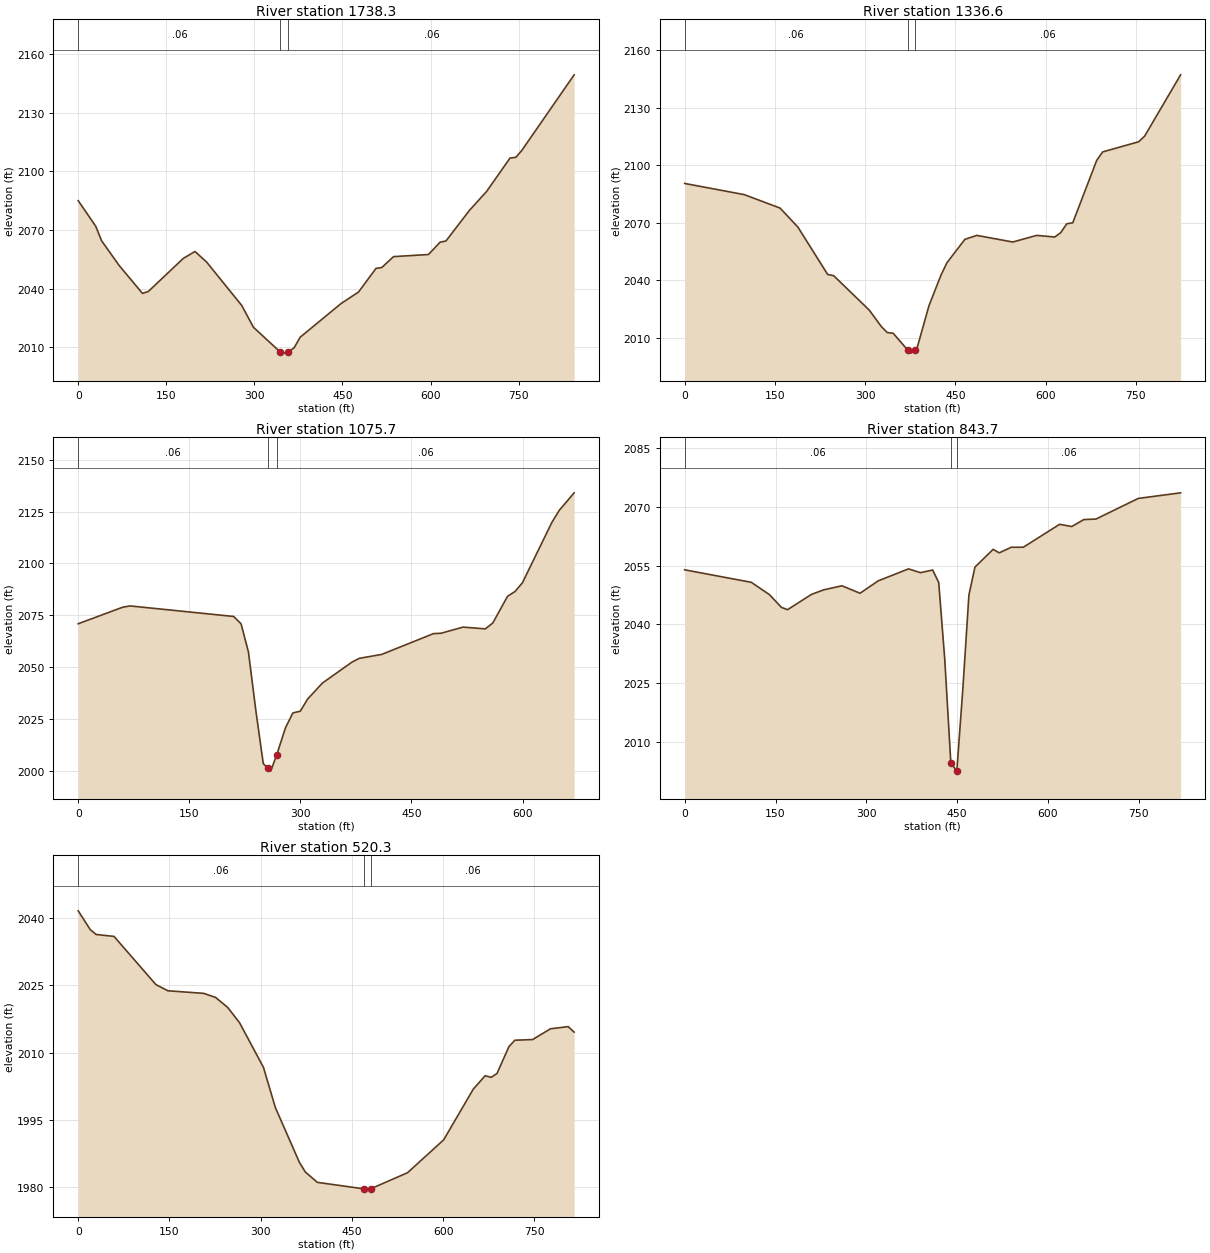
Type RM Length L Ch R = 1 ,1738.3  ,423.9,401.7,379.4
XS GIS Cut Line= 3
     1938985.977      181119.115     1938533.981      181272.868
     1938334.299      181580.939
#Sta/Elev= 30
       0 2084.97    29.8 2071.92    39.8 2064.49    69.6  2051.9   109.4 2037.59
   119.4 2038.56     179 2055.47   198.9    2059   218.8 2053.55   278.5  2031.4
   298.4 2020.27   344.4 2007.51   348.1 2007.04   358.1 2007.48     368 2009.91
     378 2015.17   447.6 2032.38   477.4 2038.27   507.2 2050.37   517.1 2050.81
     537 2056.37   596.5 2057.45   616.3 2063.76   626.3 2064.36     666 2079.91
   695.7 2089.76   735.4 2106.77   745.3 2107.12   755.3 2110.58   844.6  2149.3
#Mann= 3 , 0 , 0
       0     .06       0   344.4    .045       0   358.1     .06       0
Bank Sta=344.4,358.1
XS Rating Curve= 0 ,0
Exp/Cntr=0.3,0.1

Type RM Length L Ch R = 1 ,1336.6  ,261.6,261,260.4
XS GIS Cut Line= 3
     1938407.963      180767.996     1938323.674      181175.369
     1938230.503      181572.962
#Sta/Elev= 30
       0 2090.55      99 2084.72   158.5 2077.71   188.2 2067.79   237.7 2043.08
   247.6 2042.46     307 2024.43   326.9 2015.89   336.8 2012.78   346.7 2012.39
   370.4 2003.76   376.4 2002.04   382.4 2003.65   386.3  2004.7   406.1 2026.78
     426 2042.69   435.9 2049.15   465.8  2061.4   485.7 2063.45   545.5    2060
   585.3 2063.46   615.2  2062.6   625.2 2064.92   635.1 2069.52   645.1 2070.02
   684.9 2102.57   694.9 2107.01   754.6 2112.28   764.6 2115.24   824.4 2147.21
#Mann= 3 , 0 , 0
       0     .06       0   370.4    .045       0   382.4     .06       0
Bank Sta=370.4,382.4
XS Rating Curve= 0 ,0
Exp/Cntr=0.3,0.1

Type RM Length L Ch R = 1 ,1075.7  ,220.9,232,243.1
XS GIS Cut Line= 2
     1938124.591      180815.314     1938007.887      181474.784
#Sta/Elev= 30
       0 2070.95      60 2078.91      70 2079.54   209.9 2074.46   219.9 2070.94
   229.9 2057.29   239.9 2029.08   249.9 2003.57   255.9  2001.4   259.9 1999.96
   267.9 2007.63   279.9 2020.83   289.9 2028.01   299.9 2028.83   309.9 2034.73
   329.9 2042.42   369.8  2052.5   379.8 2054.31   409.8 2056.18   479.8  2066.2
   489.8 2066.37   519.8 2069.34   549.8 2068.49   559.8  2071.3   579.8  2084.2
   589.8 2086.46   599.8 2090.66   639.7 2119.83   649.7 2125.62   669.7 2134.02
#Mann= 3 , 0 , 0
       0     .06       0   255.9    .045       0   267.9     .06       0
Bank Sta=255.9,267.9
XS Rating Curve= 0 ,0
Exp/Cntr=0.3,0.1

Type RM Length L Ch R = 1 ,843.7   ,308.5,323.2,338
XS GIS Cut Line= 3
     1938175.388      180611.581     1937911.785      180924.955
     1937648.182       181238.33
#Sta/Elev= 30
       0 2053.92   109.9 2050.73   139.8  2047.6   159.8 2044.32   169.8 2043.72
   209.7 2047.66   229.7  2048.8   259.7 2049.84   289.6 2047.93   319.6  2051.1
   369.6 2054.16   389.5 2053.19   409.5 2053.87   419.5  2050.7   429.5 2031.05
   439.5 2004.62   449.4 2002.44   459.4 2023.53   469.4  2047.5   479.4 2054.62
   509.4 2059.16   519.4 2058.26   539.3 2059.69   559.3  2059.7   619.2 2065.56
   639.2 2064.99   659.2 2066.77   679.2  2066.9   749.1 2072.18     819 2073.61
#Mann= 3 , 0 , 0
       0     .06       0   439.5    .045       0   449.4     .06       0
Bank Sta=439.5,449.4
XS Rating Curve= 0 ,0
Exp/Cntr=0.3,0.1

Type RM Length L Ch R = 1 ,520.3   ,526.5,520.2,513.9
XS GIS Cut Line= 4
     1938130.148      180613.398     1937794.856      180689.348
     1937544.523      180747.534     1937402.138      180907.937
#Sta/Elev= 30
       0 2041.64    19.6 2037.48    29.5 2036.36    58.9 2035.93   127.7 2025.18
   147.3  2023.8   206.3 2023.22   225.9 2022.31   245.6  2020.1   265.2 2016.68
   304.5 2006.72   324.1 1997.74   363.6 1985.52   373.4 1983.34   393.2 1981.04
   469.8 1979.59   472.3 1979.53   481.8 1979.66   541.5  1983.2   600.8 1990.53
   649.5 2001.85     669 2004.84   678.8 2004.48   688.5 2005.34     708 2011.31
   717.8 2012.76     747 2012.91   776.3 2015.31   805.5  2015.8   815.3 2014.57
#Mann= 3 , 0 , 0
       0     .06       0   469.8    .045       0   481.8     .06       0
Bank Sta=469.8,481.8
XS Rating Curve= 0 ,0
Exp/Cntr=0.3,0.1

Chan Stop Cuts=-1
Use User Specified Reach Order=0
Composite Channel Slope=5